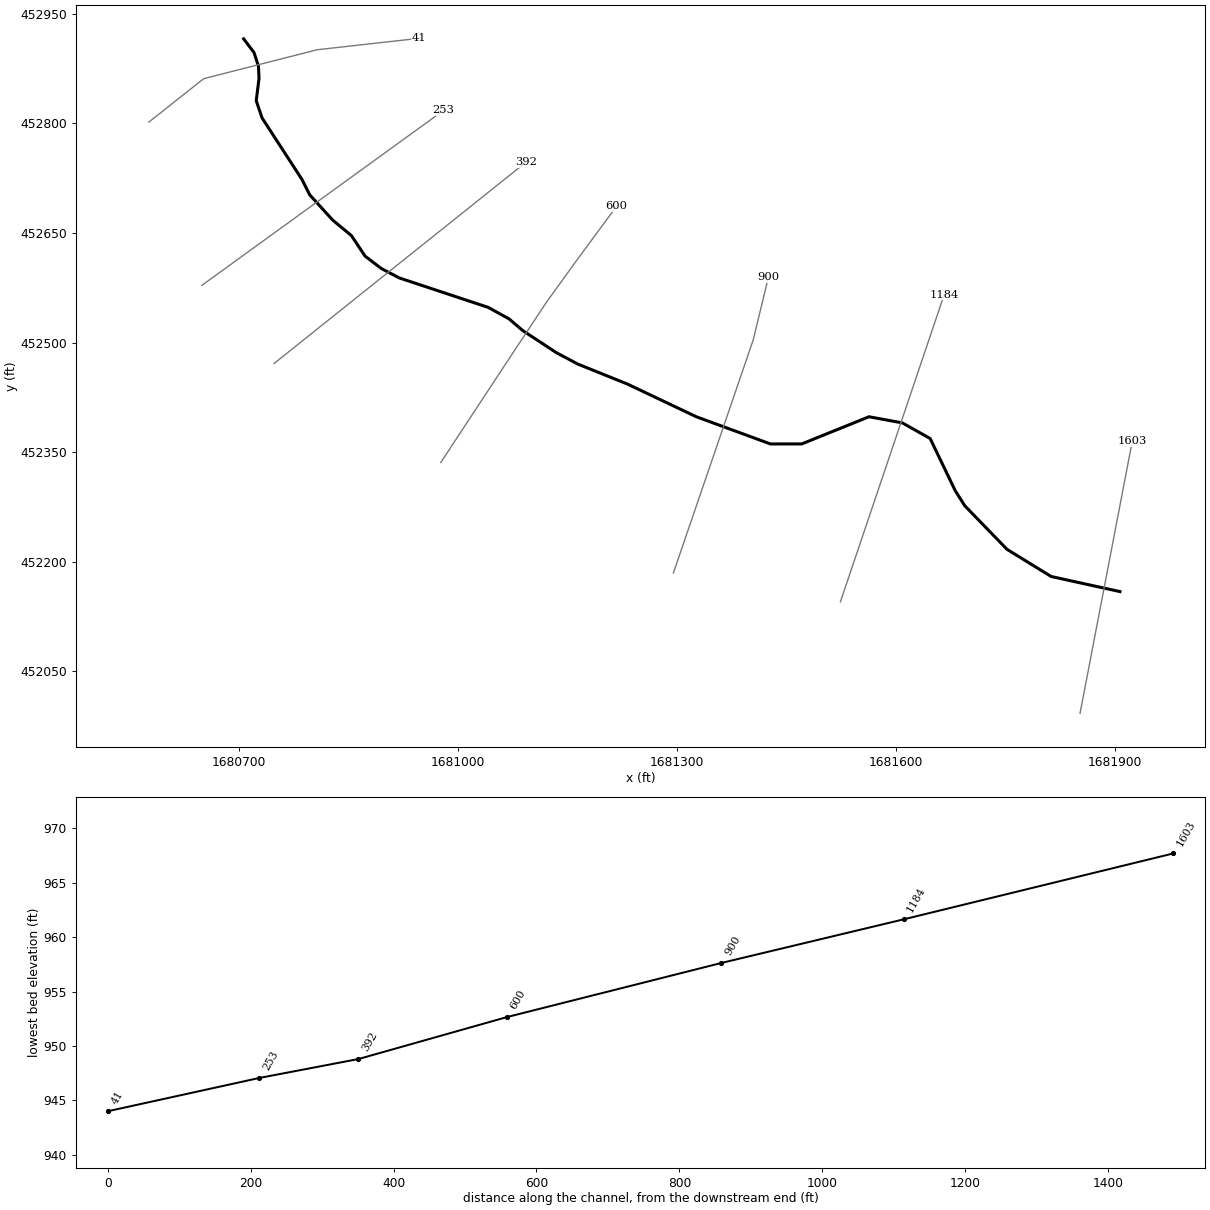
--- KnbRn.prj (project) ---

Proj Title=KnbRn
Current Plan=p01
Default Exp/Contr=0.3,0.1
English Units
Geom File=g01
Flow File=f01
Plan File=p01
Y Axis Title=Elevation
X Axis Title(PF)=Main Channel Distance
X Axis Title(XS)=Station
BEGIN DESCRIPTION:
---------- MODELED AS PART OF WVEM CTP PROGRAM, 2025----------
Stream Name: Knob Creek
Flood Zone: AFH
Marshall County, WV
HEC-RAS Version: RAS 6.6
Vertical Datum: NAVD88
Projection: NAD 1983 StatePlane West Virginia N FIPS 4701 (US Feet)
Terrain: 1-meter West Virginia FEMA R3 South Central (collected 2018-2019)
Land Use: 2024 NLCD
Hydrologic Method:
Duda et al., "Estimation of magnitude and frequency of floods for rural, unregulated streams in and near Virginia and West Virginia." September 8, 2025.
Additional Model Notes:
None
END DESCRIPTION:
DSS File=dss
DSS Export Rating Curves= 0
DSS Export Rating Curve Sorted= 0
DSS Export Volume Flow Curves= 0
DXF OffsetX= 0
DXF OffsetY= 0
DXF ScaleX= 1
DXF ScaleY= 10

--- KnbRn.p01 (plan) ---

Plan Title=Floodplain
Program Version=6.60
Short Identifier=Floodplain
Geom File=g01
Flow File=f01
Subcritical Flow
K Sum by GR= 0
Std Step Tol= 0.01
Critical Tol= 0.01
Num of Std Step Trials= 20
Max Error Tol= 0.3
Flow Tol Ratio= 0.001
Split Flow NTrial= 30
Split Flow Tol= 0.02
Split Flow Ratio= 0.02
Log Output Level= 0
Friction Slope Method= 1
Unsteady Friction Slope Method= 2
Unsteady Bridges Friction Slope Method= 1
Parabolic Critical Depth
Global Vel Dist= 0 , 0 , 0
Global Log Level= 0
CheckData=True
Encroach Param=-1 ,0,0, 0
Flow Ratio Tolerance=0.1
Flow Ratio Min Ratio=0.5
Flow Ratio Max Ratio=4
Flow Ratio Max Iterations= 10
Computation Interval=1MIN
Output Interval=1HOUR
Instantaneous Interval=1HOUR
Mapping Interval=1HOUR
Computation Time Step Use Courant=        0
Computation Time Step Use Time Series=    0
Computation Time Step Count To Double=0
Computation Time Step Max Doubling=0
Computation Time Step Max Halving=0
Computation Time Step Residence Courant=0
Run HTab= 0
Run UNet= 0
Run Sediment= 0
Run PostProcess= 0
Run WQNet= 0
Run RASMapper=-1
UNET Theta= 1
UNET Theta Warmup= 1
UNET ZTol= 0.02
UNET ZSATol= 0.02
UNET MxIter= 20
UNET Max Iter WO Improvement= 0
UNET MaxInSteps= 0
UNET DtIC= 0
UNET DtMin= 0
UNET MaxCRTS= 20
UNET WFStab= 2
UNET SFStab= 1
UNET WFX= 1
UNET SFX= 1
UNET Gravity=32.17405
UNET 1D Methodology=Finite Difference
UNET DSS MLevel= 4
UNET Pardiso=0
UNET DZMax Abort= 100
UNET Use Existing IB Tables=-1
UNET Froude Reduction=False
UNET Froude Limit= 0.8
UNET Froude Power= 4
UNET D1 Cores= 0
UNET WindReference=Eulerian
UNET WindDragFormulation=Hsu (1988)
UNET D2 Coriolis=0
UNET D2 Cores= 0
UNET D2 Theta= 1
UNET D2 Theta Warmup= 1
UNET D2 Z Tol= 0.01
UNET D2 Volume Tol= 0.01
UNET D2 Max Iterations= 20
UNET D2 Advanced Convergence=0
UNET D2 WS Max Tol=0.15
UNET D2 WS RMS Tol=0.002
UNET D2 WS Stall Tol=1
UNET D2 Equation= 0
UNET D2 RampUpFraction=0.1
UNET D2 TimeSlices= 1
UNET D2 Turbulence Formulation=None
UNET D2 Eddy Viscosity=0.3
UNET D2 Transverse Eddy Viscosity=0.1
UNET D2 Smagorinsky Mixing=0.05
UNET D2 BCVolumeCheck=0
UNET D2 Cores=0
UNET D2 SolverType=PARDISO (Direct)
UNET D2 Minimum Iterations= 3
UNET D2 Maximum Iterations= 30
UNET D2 Restart Number= 10
UNET D2 Relaxation Coeff=1.3
UNET D2 SOR Precondition Iterations= 10
UNET D2 ILUT Maximum Fill= 8
UNET D2 ILUT Tolerance=1E-08
UNET D2 Convergence Tolerance=0.00001
PS Theta= 1
PS WS Tol= 0.01
PS Volume Tol= 0.01
PS Max Iterations= 20
PS Equation= 0
PS Advance Time Step=-1
PS Target Courant=0.9
PS Time Slices= 1
PS Iterate With 2D=0
PS Project Initial WSE from DS=-1
PS Ramp Up Initial WSE from US=-1
PS Cores=0
UNET D1D2 MaxIter= 0
UNET D1D2 ZTol=0.01
UNET D1D2 QTol=0.1
UNET D1D2 MinQTol=1
DSS File=dss
Write IC File= 0
Write IC File at Fixed DateTime=0
Write IC File at Sim End=0
Echo Input=False
Echo Parameters=False
Echo Output=False
Write Detailed= 0
HDF Write Warmup=0
HDF Write Time Slices=0
HDF Flush=0
HDF Compression= 1
HDF Chunk Size= 1
HDF Spatial Parts= 1
HDF Use Max Rows=0
HDF Fixed Rows= 1
Calibration Method= 0
Calibration Iterations= 20
Calibration Max Change=0.05
Calibration Tolerance=0.2
Calibration Maximum=1.5
Calibration Minimum=0.5
Calibration Optimization Method= 1
WQ AD Non Conservative
WQ ULTIMATE=-1
WQ Max Comp Step=1HOUR
WQ Output Interval=15MIN
WQ Output Selected Increments= 0
WQ Create Restart=0
WQ Fixed Restart=0
WQ System Summary=0
WQ Write To DSS=0
Sorting and Armoring Iterations= 10
XS Update Threshold= 0.02
Bed Roughness Predictor= 0
Processes Affected by Predictor=Sediment Only
Hydraulics Update Threshold= 0.02
Energy Slope Method= 1
Volume Change Method= 1
Sediment Retention Method= 0
Sediment TS Multiplier= 1
Warm Up Method= 0
XS Weighting Method= 0
Number of US Weighted Cross Sections= 1
Number of DS Weighted Cross Sections= 1
Upstream XS Weight=0
Main XS Weight=1
Downstream XS Weight=0
Number of DS XS's Weighted with US Boundary= 1
Upstream Boundary Weight= 1
Weight of XSs Associated with US Boundary= 0
Number of US XS's Weighted with DS Boundary= 1
Downstream Boundary Weight= 0.5
Weight of XSs Associated with DS Boundary= 0.5
Percentile Method= 0
Sediment Output Level= 3
Mass or Volume Output= 0
Output Increment Type= 1
Profile and TS Output Increment= 1
Transport Output Increment 1
XS Output Flag= 0
XS Output Increment= 10
Read HDF5 Sediment Hotstart= 0
Sediment Hotstart Type= 0
Write Gradation File= 0
Read Gradation Hotstart= 0
Write HDF5 File= 1
Write Binary Output= 1
Write DSS Sediment File= 0
DSS Sediment Output Type= 1
SV Curve= 0
Specific Gage Flag= 0
Subcell Erosion Methods= 0
Subcell Deposition Methods= 0
Advection Scheme= 1
Matrix Solver= 0
Implicit Weighting Factor= 1
Maximum Outer Loop Convergence Iterations= 5
Convergence Maximum Absolute= 0.001
Convergence RMSE= 0.0001
Grain Fractions Max Abs Error= 0.001
Max Subgrid Regions= 1
Max Subgrid Length Scale= 3.402823E+38
Initial Layer Thickness= 3
Min Layer Thickness= 0.1
Max Layer Thickness= 6
Number of Layers= 5

--- KnbRn.f01 (steady flow) ---

Flow Title=Flow
Program Version=6.60
Number of Profiles= 1
Profile Names=P100yr
River Rch & RM=KnbRn,Main            ,1603
    1120
Boundary for River Rch & Prof#=KnbRn,Main            , 1
Up Type= 0
Dn Type= 3
Dn Slope=0.059
DSS Import GetInterval= 0
DSS Import GetPeak= 0
DSS Import FillOption= 0

--- KnbRn.g01 (geometry) ---

Geom Title=Geometry
Program Version=6.60

River Reach=KnbRn           ,Main
Reach XY= 30
1681906.40933374 452159.128694191681812.24746372452179.795085222
1681751.77579989 452217.008593471681694.09481288452276.549812973
1681681.07023264452297.0172917251681646.64772931452368.652975231
1681608.50410481452390.0508983141681562.91790989452398.423913062
1681470.81474763452361.2104048131681428.01922956452361.210404813
 1681326.6129363452398.4239130621681232.09081563452443.266014978
1681164.40459931452470.5284276461681135.03818822452486.135679901
1681088.89884481452516.4837163091681070.26732039452532.388540149
1681041.75359789452548.1158708931680920.12326372452588.399582982
1680895.14956039 452601.510777221680873.29789805452618.211531222
1680854.56762056 452646.306947471680828.81373505452667.690434888
 1680797.4407663452702.1851165591680786.82727048 452723.25626865
1680732.25257647452807.3735544831680724.25029589452830.999491483
1680728.06098381 452861.484666721680727.29884622452878.251693562
1680721.20174555452896.9239003061680707.00984481452915.689938888

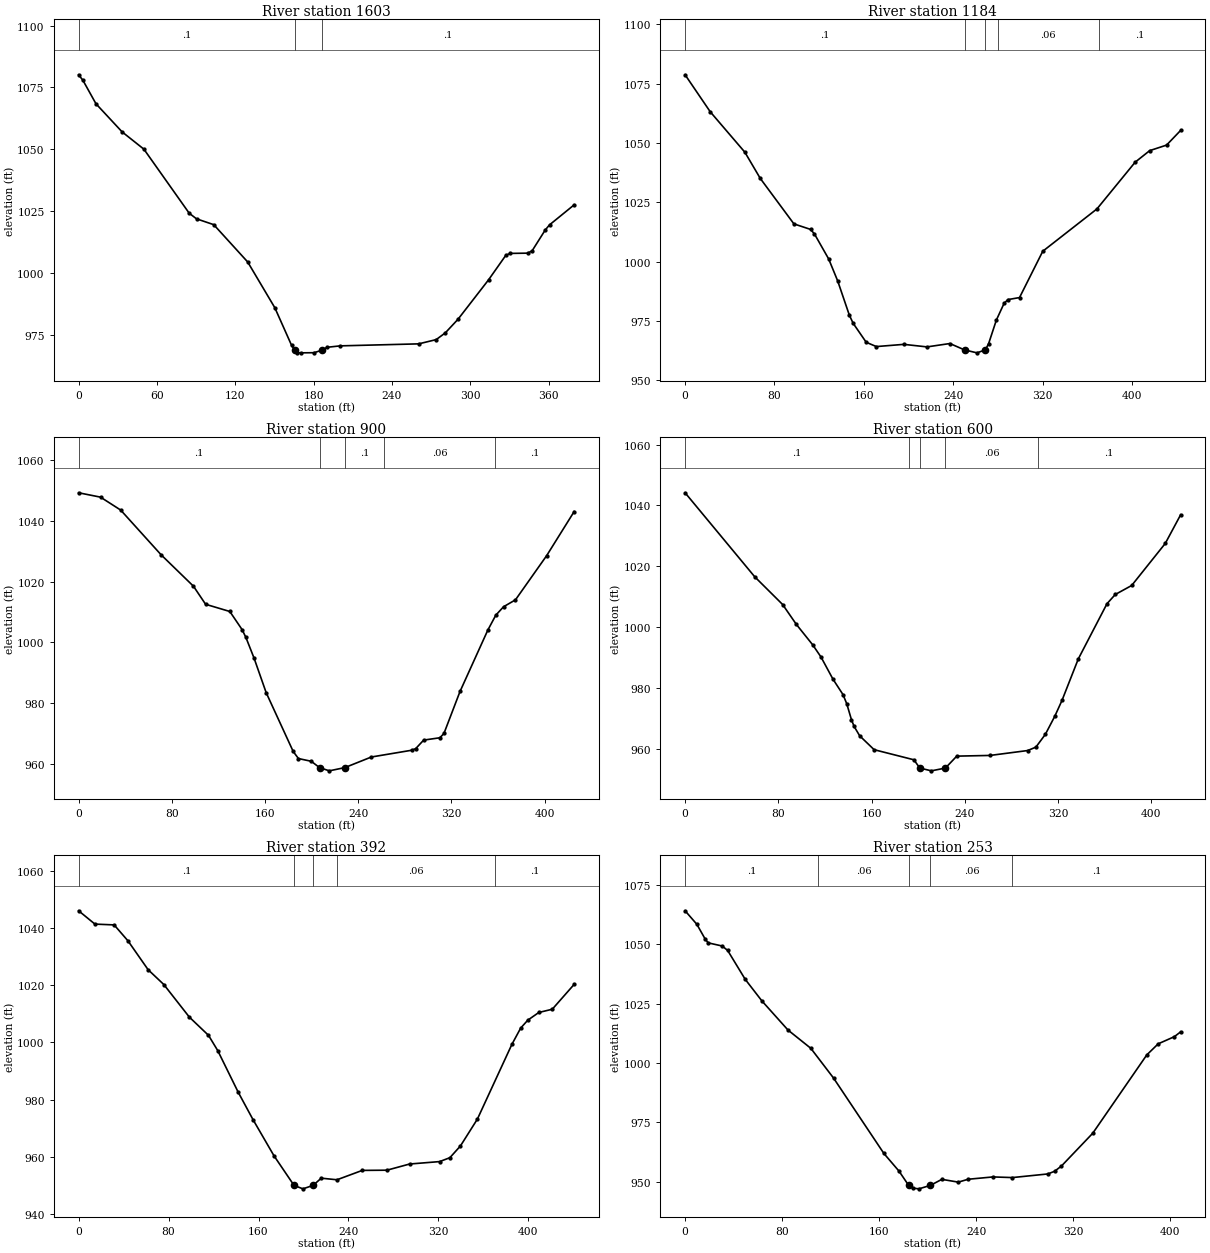
Type RM Length L Ch R = 1 ,1603    ,377.4,377.5,373.5
XS GIS Cut Line= 2
1681851.77461209451992.4427980861681923.33744657452365.196064624
#Sta/Elev= 30
       0 1080.14     3.3 1077.89    13.3  1068.4    33.3 1057.05      50 1050.05
    84.7 1024.16    90.3 1021.89   103.5 1019.53   129.5 1004.45   150.3  985.93
   163.1  970.76  165.55 968.721     167  967.79   170.3   967.7   180.3  967.75
  186.07968.7181   190.4  969.95   200.4  970.52   260.5  971.33   273.9  973.05
   280.9  975.78   290.6  981.27     314  997.21   327.3 1007.18   330.7 1007.91
     344 1008.01   347.4 1008.97   357.4 1017.35   360.7 1019.44   379.6 1027.55
#Mann= 3 ,-1,0
       0      .1       0  165.55    .045       0  186.07      .1       0
Bank Sta=165.55,186.07
XS Rating Curve= 0 ,0
Exp/Cntr(USF)=0,0
Exp/Cntr=0.3,0.1

Type RM Length L Ch R = 1 ,1184    ,253.2,255.1,251.2
XS GIS Cut Line= 2
1681523.80647157452145.1456396961681665.77498384452565.322686115
#Sta/Elev= 30
       0 1078.72    22.5 1063.14    53.5 1046.11    67.3 1035.07    97.4 1015.93
   112.3 1013.61   115.8 1011.68   128.5 1001.17   136.6  991.88     147   977.5
   150.4  974.08   162.1  966.08   171.2  964.28   195.8  965.21   216.5  964.14
     237  965.56   250.1  962.87   261.2  961.64   268.7  962.88   271.6  965.45
   278.6  975.46   285.5  982.49   288.9  984.06   299.3  984.91   320.1 1004.41
   368.6 1022.24   402.8 1041.92   415.8 1046.78   430.9 1049.11   443.5  1055.3
#Mann= 5 ,-1,0
       0      .1       0   250.1    .045       0   268.7      .1       0
     280     .06       0     370      .1       0
Bank Sta=250.1,268.7
XS Rating Curve= 0 ,0
Exp/Cntr(USF)=0,0
Exp/Cntr=0.3,0.1

Type RM Length L Ch R = 1 ,900     ,302.1,299.9,296.5
XS GIS Cut Line= 6
1681295.19600442452184.5670573411681323.54502909452267.347403586
1681347.84452118452338.3019860831681380.24406268452432.907768011
1681404.54355475 452503.862022431681425.23281784452589.265723005
#Sta/Elev= 30
       0 1049.28    18.8 1047.84    36.1 1043.58    70.8 1028.84    98.6 1018.47
     109 1012.53   129.8 1010.15   140.3 1004.19   143.6  1001.6   150.6  994.78
     161  983.39   184.2  964.01   188.7  961.68   199.7  960.78  206.78958.7012
   215.2  957.63  228.56 958.702   251.3  962.19   285.8  964.41   289.3  964.93
   296.2  967.76   310.1  968.53   313.6  969.94   327.4  983.79   351.3 1004.04
   358.1 1008.92   364.8 1011.72     375 1013.99   401.8 1028.57   425.4  1043.1
#Mann= 5 ,-1,0
       0      .1       0  206.78    .045       0  228.56      .1       0
   262.5     .06       0   357.5      .1       0
Bank Sta=206.78,228.56
XS Rating Curve= 0 ,0
Exp/Cntr(USF)=0,0
Exp/Cntr=0.3,0.1

Type RM Length L Ch R = 1 ,600     ,209.8,208,205.9
XS GIS Cut Line= 6
1680976.84920017452335.837096006 1681024.9330935452408.941280499
1681066.14790609452471.6019163431681121.34858309452554.986592084
1681165.29698601452615.8486750871681217.35823359452686.336723089
#Sta/Elev= 30
       0 1044.18    59.7 1016.55    83.7  1007.4    95.5 1000.84   109.5  994.13
   116.6  990.13   126.9  982.82   135.5  977.75   138.7  974.75   142.7  969.55
     145  967.29   149.8  964.19   162.2  959.62   196.3   956.3  201.42953.5751
   211.3  952.66  223.36 953.574   233.1   957.5   261.7  957.73   293.9  959.34
     301  960.46   309.1  964.66   317.2  970.61   323.4  975.84   337.4  989.51
     362 1007.66   369.1  1010.7   383.2 1013.67     412  1027.5   425.2 1036.94
#Mann= 5 ,-1,0
       0      .1       0   192.5     .06       0  201.42    .045       0
  223.36     .06       0   302.5      .1       0
Bank Sta=201.42,223.36
XS Rating Curve= 0 ,0
Exp/Cntr(USF)=0,0
Exp/Cntr=0.3,0.1

Type RM Length L Ch R = 1 ,392     ,138.8,138.7,138.1
XS GIS Cut Line= 2
1680748.68473179452471.3510295471681093.03718364452746.495390587
#Sta/Elev= 30
       0 1046.04    14.5 1041.38    31.6  1041.1    43.9 1035.52    61.8 1025.44
    75.8 1020.24    98.5 1008.85   115.5 1002.49   123.7  997.17   141.9  982.62
   155.1  973.01   173.8  960.34  191.59  950.01   199.5   948.8  208.53     950
   215.8  952.53   229.8  951.97   252.3  955.25   274.2  955.32   294.4  957.48
   321.1  958.33   330.2  959.69   339.6  963.79   354.7   973.2   385.4  999.34
   393.2 1005.02   399.5 1007.78   409.3 1010.47   421.3 1011.61440.7755 1020.31
#Mann= 5 ,-1,0
       0      .1       0  191.59    .045       0  208.53      .1       0
     230     .06       0     370      .1       0
Bank Sta=191.59,208.53
XS Rating Curve= 0 ,0
Exp/Cntr(USF)=0,0
Exp/Cntr=0.3,0.1

Type RM Length L Ch R = 1 ,253     ,214.5,212.2,208.2
XS GIS Cut Line= 2
1680649.59180136452578.1017969371680980.71697459452817.766250253
#Sta/Elev= 30
       0 1064.02     9.7 1058.33    16.7    1052    19.1 1050.52    30.6  1049.2
    35.1 1047.34    49.6 1035.18    63.4 1026.08    84.9 1013.85   103.7 1006.18
   122.5  993.63     164  961.94   176.5  954.49  184.47  948.48   188.3  947.33
   192.9  947.06   202.4  948.53   211.8  951.05   225.4  949.88   233.5  951.09
     254  952.07     270   951.8   299.2  953.32   304.8  954.44   310.5  956.67
   336.3  970.45   380.9 1003.41   390.3 1008.06   403.6 1011.06   408.8 1013.09
#Mann= 5 ,-1,0
       0      .1       0     110     .06       0  184.47    .045       0
   202.4     .06       0     270      .1       0
Bank Sta=184.47,202.4
XS Rating Curve= 0 ,0
Exp/Cntr(USF)=0,0
Exp/Cntr=0.3,0.1

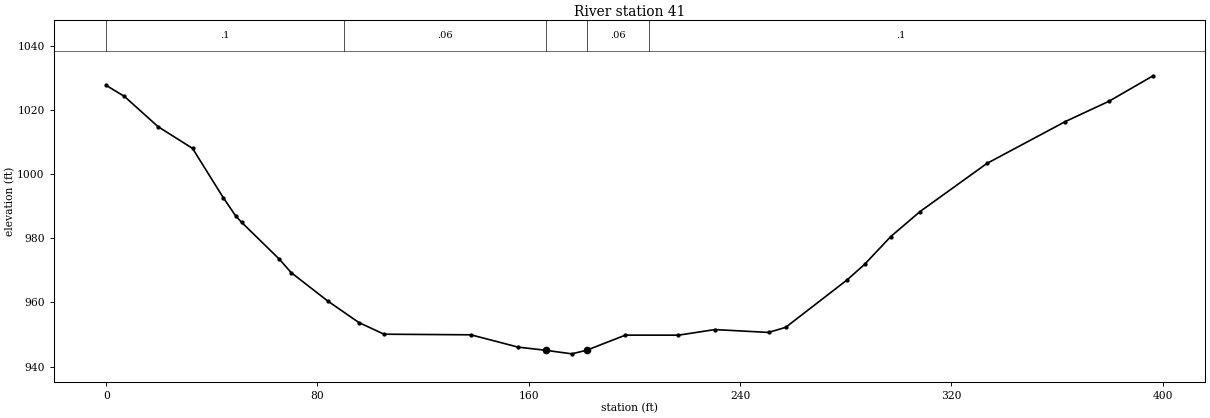
Type RM Length L Ch R = 1 ,41      ,,,
XS GIS Cut Line= 4
 1680577.3376132452801.7516098731680652.35993386  452861.1442804
1680807.61445857452900.7393940841680947.23933314452916.369044222
#Sta/Elev= 30
       0 1027.65     6.9 1024.21    19.6 1014.81    32.7 1008.01    44.3   992.7
      49  987.01    51.3  984.96    65.6  973.47      70  969.34      84  960.39
    95.7  953.74   105.2  950.12   138.1  949.93     156  946.09  166.44945.1083
   176.3     944  181.89945.1077   196.6  949.83   216.7  949.82   230.5  951.56
   250.8  950.67   257.3  952.26   280.6  967.07   287.2  971.91   297.1  980.56
   308.2  988.35   333.5 1003.33   363.2 1016.38   379.7  1022.7396.4071 1030.64
#Mann= 5 ,-1,0
       0      .1       0      90     .06       0  166.44    .045       0
  181.89     .06       0  205.69      .1       0
Bank Sta=166.44,181.89
XS Rating Curve= 0 ,0
Exp/Cntr(USF)=0,0
Exp/Cntr=0.3,0.1
LCMann Table=0

Chan Stop Cuts=-1
Use User Specified Reach Order=0
Composite Channel Slope=5